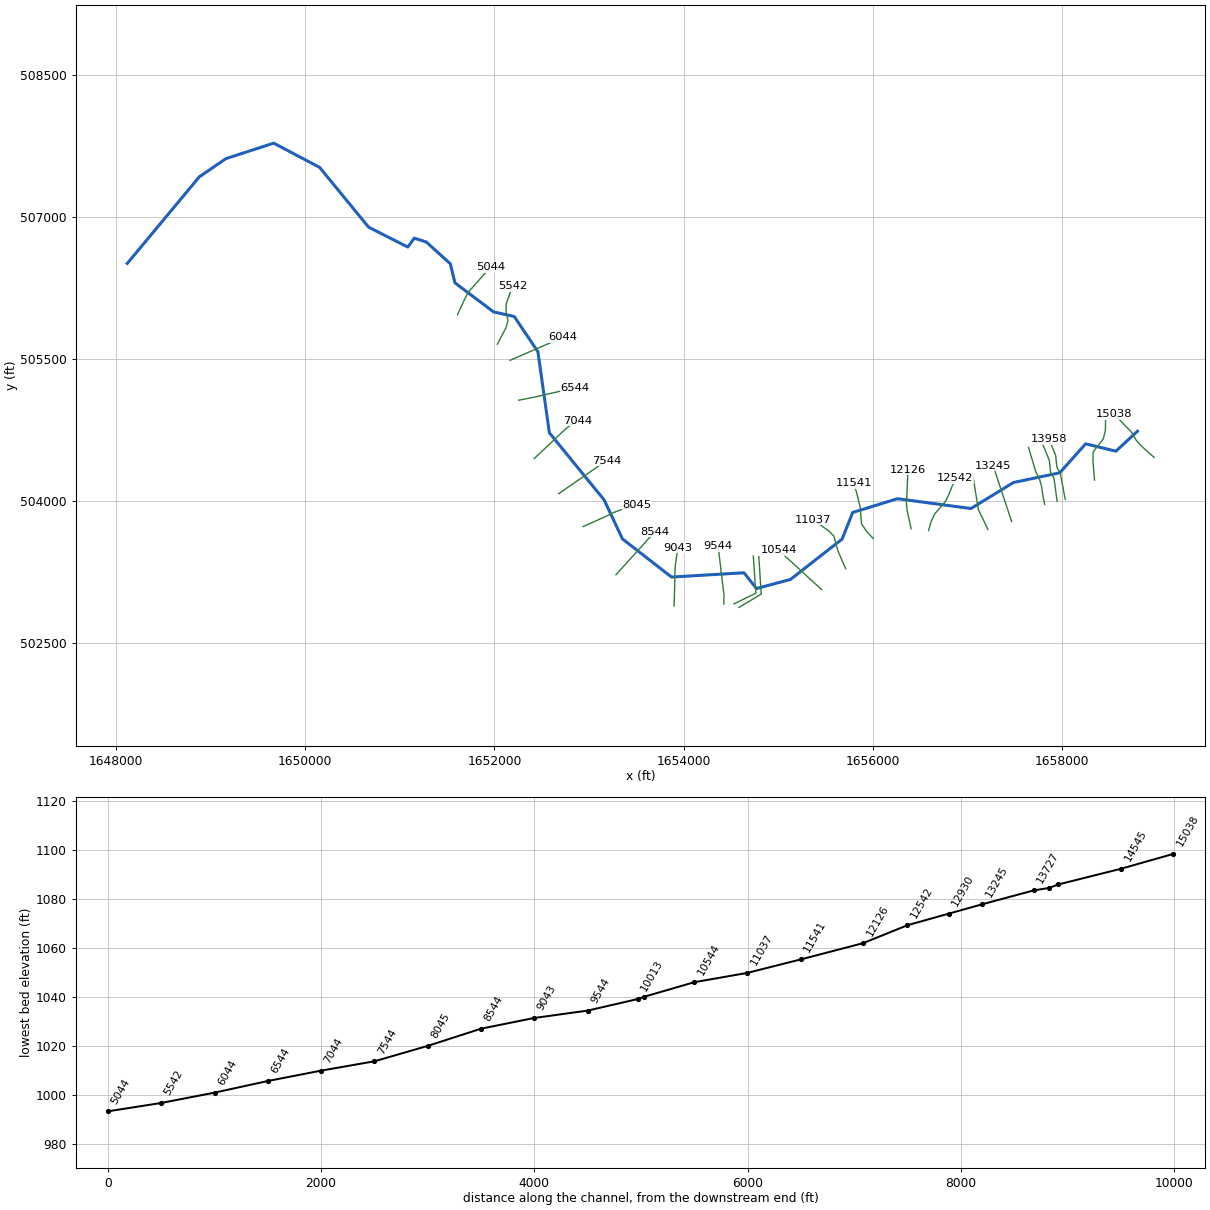
--- MidGraveCk.prj (project) ---

Proj Title=MidGraveCk
Current Plan=p01
Default Exp/Contr=0,0
English Units
Geom File=g01
Flow File=f01
Plan File=p01
BEGIN DESCRIPTION:
---------- MODELED AS PART OF WVEM CTP PROGRAM, 2025----------
Stream Name:Middle Grave Creek
Flood Zone: AFH
Marshall County, WV
HEC-RAS Version: RAS 6.6
Vertical Datum: NAVD88
Projection: NAD 1983 StatePlane West Virginia N FIPS 4701 (US Feet)
Terrain: 1-meter West Virginia FEMA R3 South Central (collected 2018-2019)
Land Use: 2024 NLCD
Hydrologic Method:
Duda et al., "Estimation of magnitude and frequency of floods for rural, unregulated streams in and near Virginia and West Virginia." September 8, 2025.
Additional Model Notes:
KWSE to AE tie-in
END DESCRIPTION:
DSS Export Rating Curves= 0
DSS Export Rating Curve Sorted= 0
DSS Export Volume Flow Curves= 0
DXF OffsetX= 0
DXF OffsetY= 0
DXF ScaleX= 0
DXF ScaleY= 0

--- MidGraveCk.p01 (plan) ---

Plan Title=Floodplain
Program Version=6.60
Short Identifier=Floodplain
Geom File=g01
Flow File=f01
Subcritical Flow
K Sum by GR= 0
Std Step Tol= 0.01
Critical Tol= 0.01
Num of Std Step Trials= 20
Max Error Tol= 0.3
Flow Tol Ratio= 0.001
Split Flow NTrial= 30
Split Flow Tol= 0.02
Split Flow Ratio= 0.02
Log Output Level= 0
Friction Slope Method= 1
Unsteady Friction Slope Method= 2
Unsteady Bridges Friction Slope Method= 1
Parabolic Critical Depth
Global Vel Dist= 0 , 0 , 0
Global Log Level= 0
CheckData=False
Encroach Param=-1 ,0,0, 0
Flow Ratio Tolerance=0.1
Flow Ratio Min Ratio=0.5
Flow Ratio Max Ratio=4
Flow Ratio Max Iterations= 10
Mapping Interval=1HOUR
Computation Time Step Use Courant=        0
Computation Time Step Use Time Series=    0
Computation Time Step Count To Double=0
Computation Time Step Max Doubling=0
Computation Time Step Max Halving=0
Computation Time Step Residence Courant=0
Run HTab= 0
Run UNet= 0
Run Sediment= 0
Run PostProcess= 0
Run WQNet= 0
Run RASMapper=-1
UNET Theta= 0
UNET Theta Warmup= 0
UNET ZTol= 0
UNET ZSATol= 0
UNET MxIter= 0
UNET Max Iter WO Improvement= 0
UNET MaxInSteps= 0
UNET DtIC= 0
UNET DtMin= 0
UNET MaxCRTS= 0
UNET WFStab= 0
UNET SFStab= 0
UNET WFX= 1
UNET SFX= 1
UNET Gravity=32.17405
UNET 1D Methodology=Finite Difference
UNET DSS MLevel= 1
UNET Pardiso=0
UNET DZMax Abort= 0
UNET Use Existing IB Tables= 0
UNET Froude Reduction=False
UNET Froude Limit= 0
UNET Froude Power= 0
UNET D1 Cores= 0
UNET WindReference=Eulerian
UNET WindDragFormulation=Hsu (1988)
UNET D2 Coriolis=0
UNET D2 Cores= 0
UNET D2 Theta= 1
UNET D2 Theta Warmup= 1
UNET D2 Z Tol= 0.01
UNET D2 Volume Tol= 0.01
UNET D2 Max Iterations= 20
UNET D2 Advanced Convergence=0
UNET D2 WS Max Tol=0.15
UNET D2 WS RMS Tol=0.002
UNET D2 WS Stall Tol=1
UNET D2 Equation= 0
UNET D2 RampUpFraction=0.1
UNET D2 TimeSlices= 1
UNET D2 Turbulence Formulation=Non-Conservative (original)
UNET D2 Eddy Viscosity=0.3
UNET D2 Transverse Eddy Viscosity=0.1
UNET D2 Smagorinsky Mixing=0
UNET D2 BCVolumeCheck=0
UNET D2 Cores=0
UNET D2 SolverType=PARDISO (Direct)
UNET D2 Minimum Iterations= 3
UNET D2 Maximum Iterations= 30
UNET D2 Restart Number= 10
UNET D2 Relaxation Coeff=1.3
UNET D2 SOR Precondition Iterations= 10
UNET D2 ILUT Maximum Fill= 8
UNET D2 ILUT Tolerance=1E-08
UNET D2 Convergence Tolerance=0.00001
PS Theta= 1
PS WS Tol= 0.01
PS Volume Tol= 0.01
PS Max Iterations= 20
PS Equation= 0
PS Advance Time Step=-1
PS Target Courant=0.9
PS Time Slices= 1
PS Iterate With 2D=0
PS Project Initial WSE from DS=-1
PS Ramp Up Initial WSE from US=-1
PS Cores=0
UNET D1D2 MaxIter= 0
UNET D1D2 ZTol=0.01
UNET D1D2 QTol=0.1
UNET D1D2 MinQTol=1
Write IC File= 0
Write IC File at Fixed DateTime=0
Write IC File at Sim End=0
Echo Input=False
Echo Parameters=False
Echo Output=False
Write Detailed= 0
HDF Write Warmup=0
HDF Write Time Slices=0
HDF Flush=0
HDF Compression= 1
HDF Chunk Size= 1
HDF Spatial Parts= 1
HDF Use Max Rows=0
HDF Fixed Rows= 1
Calibration Method= 0
Calibration Iterations= 20
Calibration Max Change=0.05
Calibration Tolerance=0.2
Calibration Maximum=1.5
Calibration Minimum=0.5
Calibration Optimization Method= 1
WQ AD Non Conservative
WQ ULTIMATE=-1
WQ Max Comp Step=1HOUR
WQ Output Interval=15MIN
WQ Output Selected Increments= 0
WQ Create Restart=0
WQ Fixed Restart=0
WQ System Summary=0
WQ Write To DSS=0
Sorting and Armoring Iterations= 10
XS Update Threshold= 0.02
Bed Roughness Predictor= 0
Processes Affected by Predictor=Sediment Only
Hydraulics Update Threshold= 0.02
Energy Slope Method= 1
Volume Change Method= 1
Sediment Retention Method= 0
Sediment TS Multiplier= 1
Warm Up Method= 0
XS Weighting Method= 0
Number of US Weighted Cross Sections= 1
Number of DS Weighted Cross Sections= 1
Upstream XS Weight=0
Main XS Weight=1
Downstream XS Weight=0
Number of DS XS's Weighted with US Boundary= 1
Upstream Boundary Weight= 1
Weight of XSs Associated with US Boundary= 0
Number of US XS's Weighted with DS Boundary= 1
Downstream Boundary Weight= 0.5
Weight of XSs Associated with DS Boundary= 0.5
Percentile Method= 0
Sediment Output Level= 3
Mass or Volume Output= 0
Output Increment Type= 1
Profile and TS Output Increment= 1
Transport Output Increment 1
XS Output Flag= 0
XS Output Increment= 10
Read HDF5 Sediment Hotstart= 0
Sediment Hotstart Type= 0
Write Gradation File= 0
Read Gradation Hotstart= 0
Write HDF5 File= 1
Write Binary Output= 1
Write DSS Sediment File= 0
DSS Sediment Output Type= 1
SV Curve= 0
Specific Gage Flag= 0
Subcell Erosion Methods= 0
Subcell Deposition Methods= 0
Advection Scheme= 1
Matrix Solver= 0
Implicit Weighting Factor= 1
Maximum Outer Loop Convergence Iterations= 5
Convergence Maximum Absolute= 0.001
Convergence RMSE= 0.0001
Grain Fractions Max Abs Error= 0.001
Max Subgrid Regions= 1
Max Subgrid Length Scale= 3.402823E+38
Initial Layer Thickness= 3
Min Layer Thickness= 0.1
Max Layer Thickness= 6
Number of Layers= 5

--- MidGraveCk.f01 (steady flow) ---

Flow Title=Flow
Program Version=6.60
Number of Profiles= 1
Profile Names=P100yr
River Rch & RM=MidGraveCk,Main,15038
     782
River Rch & RM=MidGraveCk,Main,11541
     961
River Rch & RM=MidGraveCk,Main,9544
    1370
River Rch & RM=MidGraveCk,Main,8045
    1420
River Rch & RM=MidGraveCk,Main,6544
    1600
River Rch & RM=MidGraveCk,Main,2544
    2270
Boundary for River Rch & Prof#=MidGraveCk,Main            , 1
Up Type= 0
Dn Type= 1
Dn Known WS=958
DSS Import GetInterval= 0
DSS Import GetPeak= 0
DSS Import FillOption= 0

--- MidGraveCk.g01 (geometry) ---

Geom Title=Geometry
Program Version=6.60

River Reach=MidGraveCk      ,Main
Reach XY= 30
     1658800.915      504735.421     1658573.248      504524.807
     1658252.707      504602.237     1657979.313      504295.792
     1657489.562      504193.298     1657039.655       503917.97
     1656262.512      504022.017     1655789.189      503876.317
     1655676.991      503594.453     1655131.151      503167.833
     1654771.577      503072.066     1654639.358      503238.477
     1653873.226      503193.192      1653353.89      503596.827
     1653159.892      504009.507     1652581.024      504718.889
     1652459.448      505576.962     1652209.553      505948.898
     1651990.302      505998.032      1651582.44      506304.984
     1651533.227      506506.898     1651278.897      506737.216
     1651151.871      506777.683     1651083.948       506683.48
     1650669.518      506893.673     1650150.699      507526.455
     1649665.175      507782.689     1649159.553      507618.636
     1648879.566      507427.1311648116.39322676506510.509563742

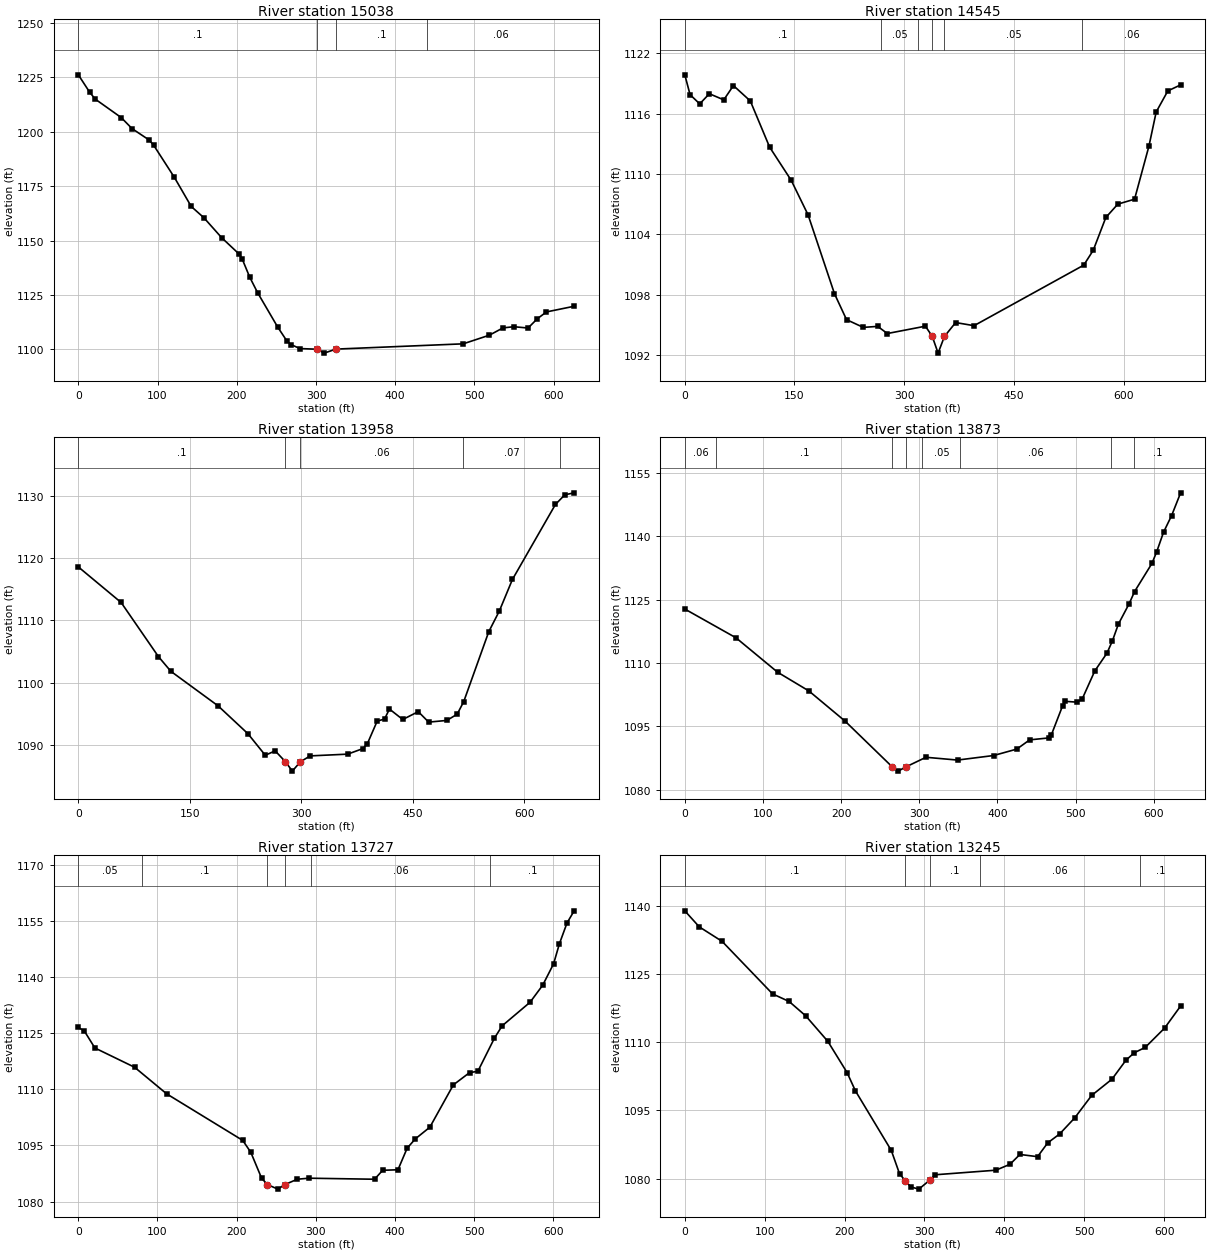
Type RM Length L Ch R = 1 ,15038   ,502.9,493,481.9
XS GIS Cut Line= 6
1658976.81281972504459.7049608981658904.58166496 504521.84295997
1658839.26716305504582.8979559841658787.98117639504640.070413813
1658736.38711947504726.7270646391658553.84122472504916.810673982
#Sta/Elev= 30
       0 1226.14    14.3 1218.15    21.3 1214.99    54.2 1206.48    67.8 1201.43
    89.4 1196.18    95.3 1193.68   121.3 1178.98   142.5 1165.65   158.4  1160.5
   180.9 1151.31   203.3 1143.66   206.7 1141.64   216.4 1133.12   226.3 1126.03
   251.7  1110.2     263 1103.99   268.3 1102.21   279.7 1100.35   301.3 1100.04
   310.3 1098.25   325.2  1100.1   485.8 1102.52     519 1106.51     536 1109.84
   549.8 1110.39   567.7 1109.78   579.3 1114.02   590.9 1117.18   625.9 1119.79
#Mann= 4 ,-1,0
       0      .1       0   301.3    .045       0   325.2      .1       0
   440.5     .06       0
Bank Sta=301.3,325.2
XS Rating Curve= 0 ,0
Exp/Cntr(USF)=0,0
Exp/Cntr=0.3,0.1

Type RM Length L Ch R = 1 ,14545   ,571.7,587.5,591.1
XS GIS Cut Line= 6
1658347.21237288504218.8635790651658329.77933688504426.429764971
1658332.40990905504516.7087838951658439.93134755504654.800699309
1658462.33189331504747.2286640551658463.41752106504856.562434897
#Sta/Elev= 30
       0 1119.85     7.2 1117.88    20.4 1116.96    33.6 1117.97    53.3 1117.36
    66.5 1118.78    89.6 1117.25     116 1112.66   145.6 1109.35   168.6 1105.92
   204.7 1098.08   221.2  1095.5   244.1 1094.73   263.8 1094.83     277 1094.12
   329.1 1094.85  338.421093.835   346.4 1092.17  355.141093.834   370.4 1095.21
   395.6  1094.9   545.6 1100.92   558.6  1102.4   575.8 1105.66   592.2 1106.99
   615.1 1107.48   634.8 1112.77   644.7 1116.16   660.6 1118.25   678.1 1118.85
#Mann= 6 ,-1,0
       0      .1       0  268.33     .05       0  318.65      .1       0
  338.42    .045       0  355.14     .05       0  543.68     .06       0
Bank Sta=338.42,355.14
XS Rating Curve= 0 ,0
Exp/Cntr(USF)=0,0
Exp/Cntr=0.3,0.1

Type RM Length L Ch R = 1 ,13958   ,84.5,84.5,84.3
XS GIS Cut Line= 6
1658037.05254204504015.2763831051657985.58062146504287.357524553
1657954.01723659504343.470208763 1657947.5876582504366.850493851
1657935.89751565504478.4913551441657864.89790155504654.037077376
#Sta/Elev= 30
       0  1118.6    57.6 1112.88   107.8 1104.18   124.5 1101.82   188.1 1096.26
   228.2 1091.79   251.6 1088.32   264.9 1089.03   278.8 1087.27     288 1085.77
   298.9 1087.28   312.1 1088.22   362.5  1088.5   382.9 1089.39     389 1090.18
   402.2 1093.81   412.1 1094.14   418.7 1095.75   436.6 1094.07   457.5 1095.33
   471.5 1093.65     496 1093.92   509.9 1094.93   518.7 1096.95   552.4 1108.19
   566.6 1111.51   584.2 1116.58   642.1 1128.64   654.7 1130.19   667.3 1130.51
#Mann= 5 ,-1,0
       0      .1       0   278.8    .045       0   298.9     .06       0
  517.93     .07       0  647.93      .1       0
Bank Sta=278.8,298.9
XS Rating Curve= 0 ,0
Exp/Cntr(USF)=0,0
Exp/Cntr=0.3,0.1

Type RM Length L Ch R = 1 ,13873   ,148.3,146.2,143.8
XS GIS Cut Line= 6
1657951.48710519503993.6161855561657918.56145699504235.348881294
1657886.99807212504291.4615655041657880.56849373504314.841850592
1657868.87835118504426.4827118851657797.87873708504602.028434117
#Sta/Elev= 30
       0 1122.78    65.5 1115.96   118.7 1107.81   158.8 1103.36   204.9 1096.24
   265.7 1085.32   272.9 1084.37  282.391085.328   308.5 1087.65   348.9 1086.99
   395.1 1088.07   424.7 1089.59   441.2 1091.78   466.5 1092.25     469 1092.99
   483.4 1099.89   486.7 1100.91   501.1 1100.72   508.2 1101.39   524.5 1108.11
   540.1 1112.33   547.1 1115.27   554.7 1119.21   568.4 1124.02   575.4 1126.92
   597.6 1133.58   603.8  1136.4   612.4 1140.96   622.8 1144.93   634.3 1150.31
#Mann= 8 ,-1,0
       0     .06       0      40      .1       0   265.7    .045       0
  282.39      .1       0  304.01     .05       0  352.64     .06       0
  544.89     .07       0  574.89      .1       0
Bank Sta=265.7,282.39
XS Rating Curve= 0 ,0
Exp/Cntr(USF)=0,0
Exp/Cntr=0.3,0.1

Type RM Length L Ch R = 1 ,13727   ,476,481.8,478.4
XS GIS Cut Line= 6
1657819.33501121503962.7204956341657799.90165113504059.460131548
1657787.69301413504148.1554922091657767.18157221504221.701604955
1657724.12588404504311.9583142181657648.63030012504562.696985967
#Sta/Elev= 30
       0  1126.5     7.5 1125.59    20.9 1121.03    71.1 1115.88   111.6 1108.78
   207.7 1096.35   217.9 1093.17   231.6 1086.23  238.941084.557     252 1083.34
  260.961084.558   276.6 1085.98   291.1 1086.26   374.2 1085.98   384.5 1088.37
   403.8 1088.51   415.4 1094.27   425.7 1096.75   444.1 1099.88   473.8 1111.18
   494.3 1114.46   504.7 1114.79   525.7 1123.66   535.4 1126.94   570.7 1133.24
   586.6 1137.77   600.4 1143.49   607.7 1148.82   617.4 1154.42   626.4 1157.65
#Mann= 6 ,-1,0
       0     .05       0      80      .1       0  238.94    .045       0
  260.96      .1       0  294.56     .06       0  520.61      .1       0
Bank Sta=238.94,260.96
XS Rating Curve= 0 ,0
Exp/Cntr(USF)=0,0
Exp/Cntr=0.3,0.1

Type RM Length L Ch R = 1 ,13245   ,311.8,315.5,310.6
XS GIS Cut Line= 2
1657470.25766267 503780.490916561657275.12816214504369.765359286
#Sta/Elev= 30
       0 1138.86    18.1 1135.34    46.7 1132.15   109.9  1120.6   130.6 1118.94
   151.3 1115.79     179 1110.19   203.2  1103.3   213.6 1099.29   258.5  1086.2
   268.8 1081.09   275.8 1079.57     283 1078.18     293  1077.7   306.9 1079.71
   313.8 1080.86   389.4 1081.86   407.1 1083.16   419.5 1085.32   441.6 1084.83
   454.3 1087.86   469.3 1089.83   488.1 1093.35   509.4  1098.3   534.8 1101.87
   552.2 1106.02   562.6 1107.66   576.4 1108.85   600.6 1113.08   620.7 1117.94
#Mann= 5 ,-1,0
       0      .1       0   275.8    .045       0   306.9      .1       0
     370     .06       0     570      .1       0
Bank Sta=275.8,306.9
XS Rating Curve= 0 ,0
Exp/Cntr(USF)=0,0
Exp/Cntr=0.3,0.1

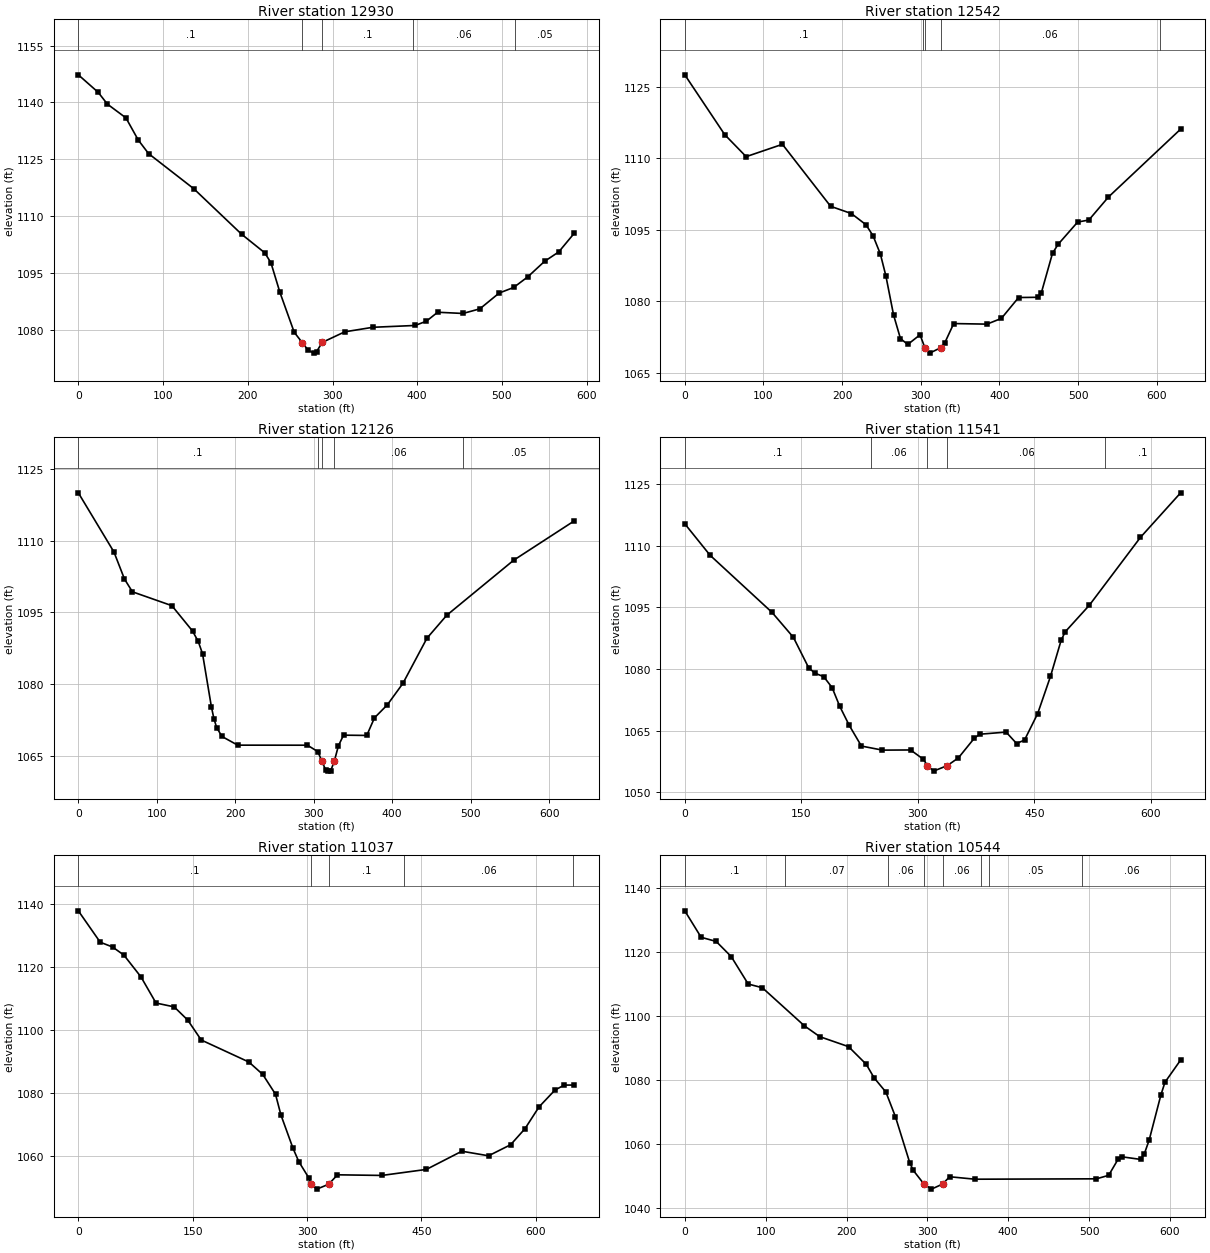
Type RM Length L Ch R = 1 ,12930   ,394.3,387.9,376.8
XS GIS Cut Line= 3
1657220.08416531 503696.365764621657118.12541099503908.505753447
1657062.21254572504253.849921304
#Sta/Elev= 30
       0  1147.3    23.4 1142.69    34.3 1139.57    56.2 1135.93    70.7  1130.1
    82.9 1126.51   136.3 1117.23   192.7 1105.23     220 1100.33   227.3 1097.71
   237.9  1089.9   254.8 1079.35   264.5 1076.57   271.2 1074.63   277.8 1073.85
   281.1  1074.2   287.8 1076.67   314.4 1079.47   347.6 1080.67   397.5 1081.15
   410.8 1082.28   424.1 1084.64     454 1084.32   473.9 1085.54   496.7 1089.71
   513.8 1091.18   530.4 1093.97   550.3 1098.08     567 1100.56   585.2 1105.46
#Mann= 5 ,-1,0
       0      .1       0   264.5    .045       0   287.8      .1       0
  395.37     .06       0  515.37     .05       0
Bank Sta=264.5,287.8
XS Rating Curve= 0 ,0
Exp/Cntr(USF)=0,0
Exp/Cntr=0.3,0.1

Type RM Length L Ch R = 1 ,12542   ,410.1,416,422.2
XS GIS Cut Line= 6
1656592.28871739503684.9148438131656618.42613231 503779.23322472
1656656.38373356503860.670397803 1656770.9120478503994.810221389
1656805.46676873 504065.542363391656874.91905764504239.592868313
#Sta/Elev= 30
       0 1127.49    50.8 1114.94      78 1110.33   124.1 1112.92   185.4 1099.92
   211.8  1098.4   230.3 1096.06   239.3 1093.76   248.6 1089.94   255.6 1085.37
   265.5 1077.09   274.2 1072.18   283.5 1070.95   299.1 1072.98  305.21 1070.27
   311.4 1069.13  325.371070.269   330.2 1071.17   341.9 1075.33   384.2 1075.21
   402.5 1076.41   424.4 1080.79   449.7 1080.84   453.3 1081.77   467.5 1090.07
   474.6 1091.94   499.5 1096.62   513.7 1097.04   538.6 1101.86   630.4  1116.1
#Mann= 5 ,-1,0
       0      .1       0  302.72     .06       0  305.21    .045       0
  325.37     .06       0  603.92     .05       0
Bank Sta=305.21,325.37
XS Rating Curve= 0 ,0
Exp/Cntr(USF)=0,0
Exp/Cntr=0.3,0.1

Type RM Length L Ch R = 1 ,12126   ,577.4,584.6,578.4
XS GIS Cut Line= 6
1656406.68564284503702.5422475171656385.64893951503804.187057345
1656364.95278667503897.3092464341656357.78088501503973.396364598
1656363.13651735504073.2951149331656374.02954017504329.255889101
#Sta/Elev= 30
       0 1119.98    45.4 1107.61    58.8 1101.96    68.9 1099.29   119.2 1096.39
   145.5  1091.1   152.8 1088.91   158.3 1086.34   169.6 1075.22   172.9 1072.69
   176.3 1070.92     183 1069.05   203.1 1067.23     292 1067.22   305.2 1065.88
   310.61063.825     315 1062.11   318.3  1061.8   321.6 1061.87  326.141063.824
   331.5 1067.12     338 1069.32   367.6 1069.26   377.4 1072.94   393.8 1075.66
   413.6 1080.13   444.3 1089.59   469.5 1094.38   554.8 1105.89   631.9  1114.1
#Mann= 5 ,-1,0
       0      .1       0  305.62     .06       0   310.6    .045       0
  326.14     .06       0  490.65     .05       0
Bank Sta=310.6,326.14
XS Rating Curve= 0 ,0
Exp/Cntr(USF)=0,0
Exp/Cntr=0.3,0.1

Type RM Length L Ch R = 1 ,11541   ,498.2,504.3,504.5
XS GIS Cut Line= 6
1656005.41882814503601.8346293871655933.84055921  503678.1218784
1655882.20549189503757.5967850541655868.61529598503932.128588229
1655828.55664906504094.3864658031655799.88577464504186.747173473
#Sta/Elev= 30
       0 1115.36    32.6  1107.7   112.4 1093.79   139.8 1087.74   159.4 1080.37
   167.2 1079.04   178.9 1078.16   189.7 1075.49   199.4 1070.99   211.8 1066.29
   227.4 1061.28   254.5 1060.29   290.7 1060.33   307.1 1058.08  312.421056.536
   320.3 1055.18  338.071056.535   352.3 1058.41   372.9 1063.22   379.8 1064.16
   413.7 1064.68   427.2  1061.9   437.4 1062.74   454.3 1069.16   470.8 1078.21
   484.6 1087.04   489.8 1089.08   520.8 1095.53   586.7 1112.07   638.4  1122.9
#Mann= 5 ,-1,0
       0      .1       0  239.39     .06       0  312.42    .045       0
  338.07     .06       0  541.65      .1       0
Bank Sta=312.42,338.07
XS Rating Curve= 0 ,0
Exp/Cntr(USF)=0,0
Exp/Cntr=0.3,0.1

Type RM Length L Ch R = 1 ,11037   ,483.7,492.6,496.4
XS GIS Cut Line= 6
1655715.09854263503281.300821647 1655640.1387188503452.540636644
1655615.97013196503526.4473129811655590.93737364503625.952363312
1655530.30954213503685.4059845661655368.74523272503799.789942145
#Sta/Elev= 30
       0 1137.89    28.7 1127.94    44.9 1126.42    59.8 1123.84    82.1 1116.96
   101.9 1108.65   125.7 1107.44   143.4 1103.27   161.2 1096.93   223.7 1089.95
   241.9 1086.01   258.6 1079.74   265.7 1073.17   281.5 1062.63   289.2 1058.35
   302.7 1053.05  305.481051.203   312.8 1049.65  328.331051.202   339.9 1054.19
   398.1 1053.99   456.5  1055.9     503 1061.67     538 1060.22     567 1063.73
   585.8 1068.81   604.3 1075.74   625.2 1081.08   637.4 1082.64   650.3 1082.65
#Mann= 5 ,-1,0
       0      .1       0  305.48    .045       0  328.33      .1       0
  427.32     .06       0  649.33     .05       0
Bank Sta=305.48,328.33
XS Rating Curve= 0 ,0
Exp/Cntr(USF)=0,0
Exp/Cntr=0.3,0.1

Type RM Length L Ch R = 1 ,10544   ,481.6,474.8,466.3
XS GIS Cut Line= 6
1655460.65154497503061.1572330591655326.25581639503183.218996808
1655197.50804238503302.1531421391655142.08098789503352.679943979
 1655076.8130738503410.9852735551655008.17902473503475.032389566
#Sta/Elev= 30
       0 1132.86    20.2 1124.59    38.8  1123.3    57.4 1118.57    78.4 1109.99
    95.9 1108.83     148 1096.91   166.9 1093.54   202.5 1090.42   224.4 1084.91
   234.1 1080.68   248.7 1076.23   260.4 1068.59   278.3 1054.08   282.6 1051.74
  295.791047.481   305.1  1045.9  318.821047.483   327.5 1049.77   358.8    1049
   509.1 1049.12   524.2 1050.21   535.8 1055.22   540.3 1056.01   563.6 1055.19
   568.3 1056.93   574.3 1061.23   588.7 1075.23   593.8 1079.28   613.2 1086.24
#Mann= 8 ,-1,0
       0      .1       0  123.88     .07       0  251.55     .06       0
  295.79    .045       0  318.82     .06       0  366.83      .1       0
  376.83     .05       0  491.83     .06       0
Bank Sta=295.79,318.82
XS Rating Curve= 0 ,0
Exp/Cntr(USF)=0,0
Exp/Cntr=0.3,0.1

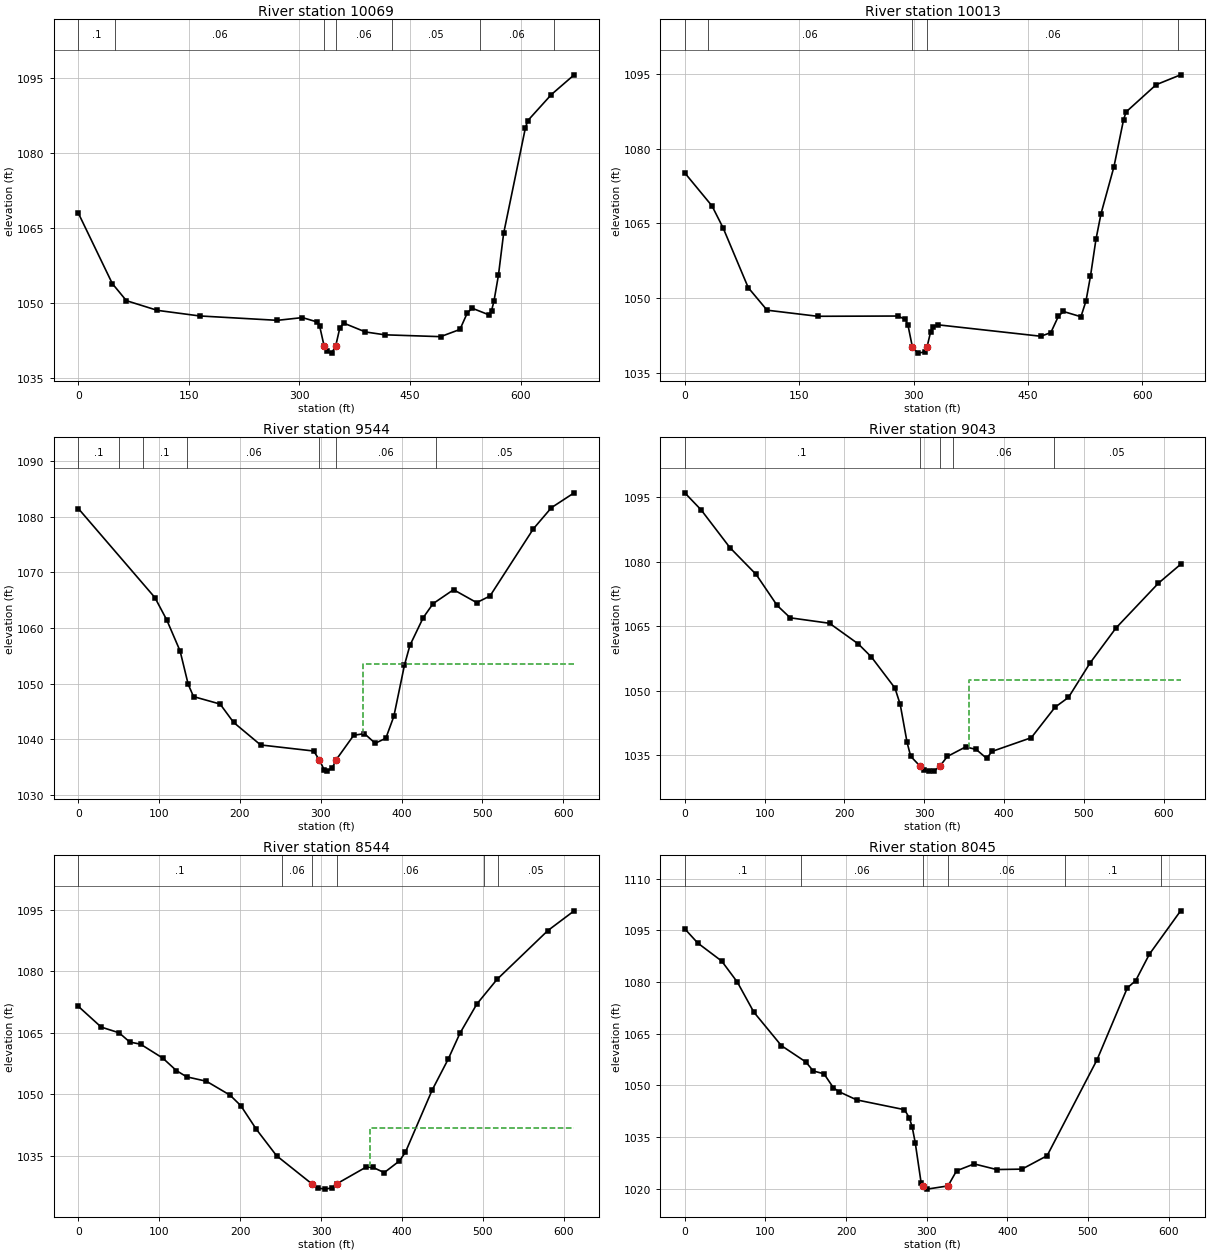
Type RM Length L Ch R = 1 ,10069   ,56.7,56.8,56.7
XS GIS Cut Line= 3
1654585.62518411502871.7024388011654821.88996286 503012.91816863
 1654796.0909353503409.408486996
#Sta/Elev= 30
       0 1067.95    46.1 1053.83    65.2 1050.41   107.2 1048.47   164.5 1047.35
     270 1046.47     304 1047.02   323.8 1046.15   327.3 1045.36  333.481041.276
   336.9 1040.25   343.5  1039.9  349.031041.278   354.6 1044.88   359.9 1045.92
   389.5 1044.14   415.8 1043.57   491.4  1043.2   517.7 1044.65   527.6 1047.94
   534.2  1048.9   557.2 1047.56   560.5 1048.39   563.8 1050.31   569.9 1055.52
   576.9 1063.87   606.5 1085.06   609.8  1086.5   641.7 1091.71   672.6 1095.66
#Mann= 7 ,-1,0
       0      .1       0      50     .06       0  333.48    .045       0
  349.03     .06       0  425.25     .05       0  545.25     .06       0
  645.25     .05       0
Bank Sta=333.48,349.03
XS Rating Curve= 0 ,0
Exp/Cntr(USF)=0,0
Exp/Cntr=0.3,0.1

Type RM Length L Ch R = 1 ,10013   ,466.9,468.6,468.6
XS GIS Cut Line= 3
1654534.02712898 502909.722058371654764.86053351503022.423073522
1654737.70366239 503414.83986122
#Sta/Elev= 30
       0 1075.11    35.7  1068.5    50.3 1064.08    83.2 1052.13   107.9 1047.62
   174.1  1046.4   279.4 1046.45   289.3 1045.76   292.6 1044.66  298.431040.264
   305.7 1039.02   315.6 1039.28  317.661040.262   322.2 1043.17   325.5 1044.33
     332 1044.69   466.9  1042.4     480 1043.13   489.9  1046.4   496.5 1047.36
   519.5 1046.31   526.1 1049.47     532 1054.45   539.2 1061.83   545.8 1066.94
   562.7 1076.31   575.4 1085.79   578.7 1087.33   618.1 1092.78   650.2 1094.76
#Mann= 5 ,-1,0
       0      .1       0      30     .06       0  298.43    .045       0
  317.66     .06       0  646.88     .05       0
Bank Sta=298.43,317.66
XS Rating Curve= 0 ,0
Exp/Cntr(USF)=0,0
Exp/Cntr=0.3,0.1

Type RM Length L Ch R = 1 ,9544    ,501.6,500.8,498.7
XS GIS Cut Line= 6
1654426.15427014502909.3766967211654428.04796714503004.042189807
 1654417.5191168503090.9065173861654408.49420047503165.361749053
1654387.43682788503339.0900761491654365.62716022503519.023115233
#Sta/Elev= 30
       0 1081.45    94.7 1065.47   109.4 1061.45   125.9 1055.87   135.9  1049.9
   142.5 1047.69   175.4 1046.35     192 1043.07   225.5 1039.01   291.2 1037.92
  298.281036.282   304.4 1034.48   307.7 1034.31   314.3 1034.91  318.631036.281
   340.7 1040.75     354 1041.04   367.2 1039.31   380.4 1040.21   390.3 1044.13
   403.5 1053.37   410.2 1056.88   426.7 1061.87   438.9 1064.38   464.2 1066.88
   492.8 1064.56   509.3 1065.75     563 1077.82   585.3 1081.61   613.4 1084.27
#Mann= 7 ,-1,0
       0      .1       0      50     .05       0      80      .1       0
  134.68     .06       0  298.28    .045       0  318.63     .06       0
  442.18     .05       0
#XS Ineff= 2 , 0
                          351.78         1053.53
Permanent Ineff=
       F       F
Bank Sta=298.28,318.63
XS Rating Curve= 0 ,0
Exp/Cntr(USF)=0,0
Exp/Cntr=0.3,0.1

Type RM Length L Ch R = 1 ,9043    ,507.8,499.2,488.3
XS GIS Cut Line= 6
1653900.05689713 502886.657582061653907.59165896 503142.79683356
1653908.98634122503242.7992582321653913.27504656503318.573056817
1653925.87213422503408.737574637 1653942.1893588503505.345649138
#Sta/Elev= 30
       0 1096.08    20.5  1092.1    56.6 1083.31    89.4 1077.08   115.7 1069.87
   132.1 1066.99   181.3 1065.72   217.4 1060.91   233.8 1057.87   263.3 1050.64
   269.9 1046.82   278.5 1037.99     283 1034.76  294.131032.591   299.4  1031.5
     306 1031.31   312.6 1031.34  320.081032.591     329 1034.73   351.9 1036.95
   365.1 1036.35   378.2 1034.28   384.8 1035.89   434.1 1039.09   463.9 1046.19
   480.7 1048.47   507.6 1056.44   540.2 1064.62   593.4 1075.05   621.2 1079.44
#Mann= 5 ,-1,0
       0      .1       0  294.13    .045       0  320.08      .1       0
  336.25     .06       0  462.16     .05       0
#XS Ineff= 2 , 0
                          355.74         1052.56
Permanent Ineff=
       F       F
Bank Sta=294.13,320.08
XS Rating Curve= 0 ,0
Exp/Cntr(USF)=0,0
Exp/Cntr=0.3,0.1

Type RM Length L Ch R = 1 ,8544    ,504.3,499,492.5
XS GIS Cut Line= 6
1653285.46724705503217.5279833081653348.33063839503287.078369141
1653524.34800288503481.8197775631653574.63792856503537.460414305
1653633.14306089503602.5255728961653695.17574522503673.115326732
#Sta/Elev= 30
       0 1071.46    28.2 1066.41    50.4 1065.01    63.6 1062.76    76.9 1062.24
   104.4 1058.84   121.1 1055.82   133.8 1054.29   158.3 1053.21   187.5 1049.82
   200.7 1047.28     220  1041.5   244.9 1035.08  288.341028.256   296.7 1027.17
     305 1026.93     313 1027.22  319.591028.255   355.5 1032.29   364.1 1032.23
     378 1030.95   396.6 1033.77   404.1 1035.88   437.2 1051.05     457 1058.58
   471.5 1064.87   492.4 1072.01   517.4 1078.03   580.2 1089.92   612.7 1094.73
#Mann= 6 ,-1,0
       0      .1       0  251.25     .06       0  288.34    .045       0
  319.59     .06       0  501.25      .1       0  518.75     .05       0
#XS Ineff= 2 , 0
                          360.09         1041.73
Permanent Ineff=
       F       F
Bank Sta=288.34,319.59
XS Rating Curve= 0 ,0
Exp/Cntr(USF)=0,0
Exp/Cntr=0.3,0.1

Type RM Length L Ch R = 1 ,8045    ,498.8,501,503.6
XS GIS Cut Line= 6
1652937.66249648503726.9872662281653171.64628047503831.675048977
1653261.24157372503876.2481225581653332.56492189503901.893084392
1653416.80917597503928.5806950631653507.60262956503954.512729809
#Sta/Elev= 30
       0 1095.42      16 1091.31    45.8 1086.06    65.2 1079.96    85.6 1071.27
   119.8 1061.54   150.2  1056.8   159.3  1054.2   172.6 1053.38   184.4  1049.3
   191.6 1048.15   213.2 1045.81   272.5 1042.97   278.5  1040.6   282.1  1037.9
   285.8 1033.43   293.1  1021.8  295.041020.856   300.4 1019.93  326.491020.858
   337.1 1025.25   358.9 1027.24   386.8 1025.61   418.2 1025.73   449.4 1029.62
   511.3 1057.43   548.9  1078.3   559.2 1080.37   576.2 1088.04     615 1100.64
#Mann= 6 ,-1,0
       0      .1       0   143.8     .06       0  295.04    .045       0
  326.49     .06       0   472.2      .1       0  590.57     .05       0
Bank Sta=295.04,326.49
XS Rating Curve= 0 ,0
Exp/Cntr(USF)=0,0
Exp/Cntr=0.3,0.1

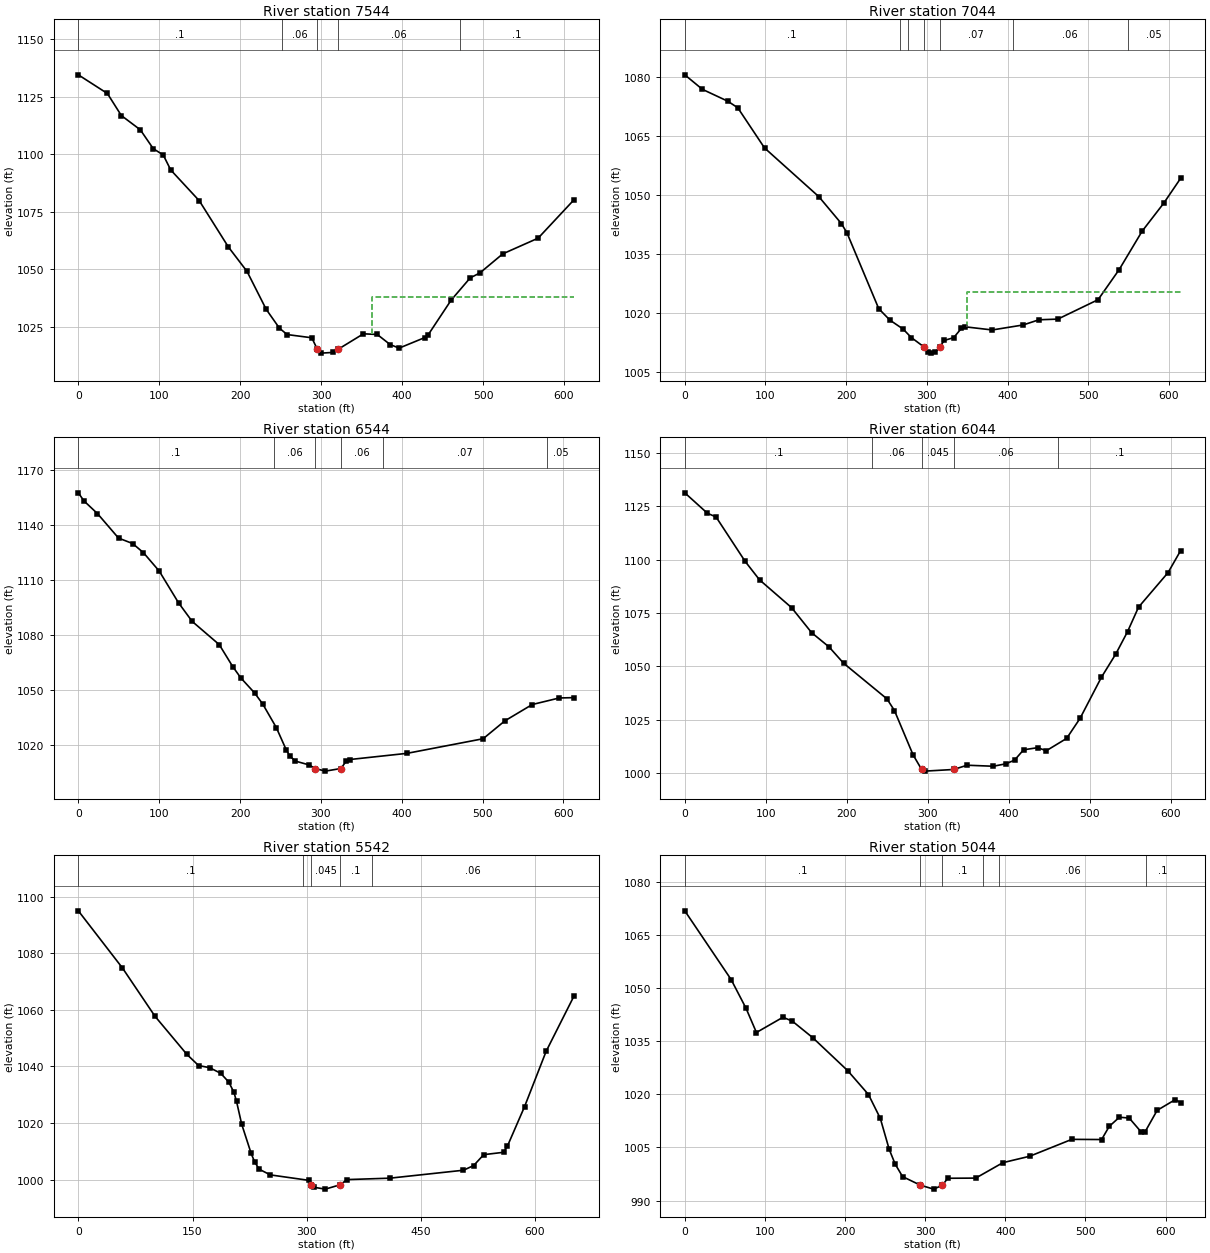
Type RM Length L Ch R = 1 ,7544    ,498.4,500,501.3
XS GIS Cut Line= 6
1652679.04752813504074.2916897241652827.88876589504177.722257137
1652971.59713989504277.5868868081653033.18658364504320.385685727
1653105.04109871504370.317016304 1653182.0294618 504423.81362848
#Sta/Elev= 30
       0 1134.56    35.9 1126.45    53.1 1116.88    76.6 1110.66    92.6 1102.46
   104.9 1099.74   114.1 1093.24   149.5  1079.8   185.4 1059.73   208.4 1049.13
     232  1032.7   248.4 1024.49   257.9  1021.7   288.4  1020.3  295.291015.269
   300.3 1013.63   314.5 1013.94  320.751015.266   352.2 1022.03   369.3 1021.73
   385.2 1017.35   396.3 1015.81   428.2 1020.42   432.4 1021.71   460.6 1036.69
   484.1 1046.33     496 1048.46   524.3 1056.76     568 1063.59   612.5 1080.34
#Mann= 5 ,-1,0
       0      .1       0  251.25     .06       0  295.29    .045       0
  320.75     .06       0  471.25      .1       0
#XS Ineff= 2 , 0
                          362.46          1038.2
Permanent Ineff=
       F       F
Bank Sta=295.29,320.75
XS Rating Curve= 0 ,0
Exp/Cntr(USF)=0,0
Exp/Cntr=0.3,0.1

Type RM Length L Ch R = 1 ,7044    ,503.9,500,495.3
XS GIS Cut Line= 6
1652421.00112823504446.6396983121652607.29799972 504622.58750914
1652679.99962597504691.2494453041652734.52543555504742.746061474
1652801.89209872504798.852248475 1652884.3017108504847.195655733
#Sta/Elev= 30
       0 1080.59    21.8  1076.9    53.4 1073.87    65.7  1072.2    98.8    1062
   166.2 1049.59     194 1042.78   200.9 1040.44   240.4 1021.11   254.3  1018.2
   270.6 1015.93   280.7 1013.79  296.81 1011.34   301.6 1010.13   305.4 1009.82
   310.6 1010.04  315.771011.341   321.6 1013.05   333.2 1013.75   342.8 1016.12
   346.7 1016.53     381 1015.71   419.3 1016.98   438.9  1018.3   462.3 1018.47
   512.2 1023.41   538.4 1031.08   566.8 1040.83   593.6 1047.96   614.5 1054.27
#Mann= 7 ,-1,0
       0      .1       0  266.25     .06       0  276.25     .07       0
  296.81    .045       0  315.77     .07       0  406.25     .06       0
  548.92     .05       0
#XS Ineff= 2 , 0
                           350.2         1025.24
Permanent Ineff=
       F       F
Bank Sta=296.81,315.77
XS Rating Curve= 0 ,0
Exp/Cntr(USF)=0,0
Exp/Cntr=0.3,0.1

Type RM Length L Ch R = 1 ,6544    ,497,500,504.4
XS GIS Cut Line= 6
 1652256.0943058505063.7050652211652348.85724364505081.672877058
1652434.64086471505099.1046007281652507.74570538505115.857519984
1652605.21926372505138.1940894721652854.99501088505195.432163984
#Sta/Elev= 30
       0 1157.34       7 1152.91    23.7    1146    49.7 1132.67    67.2 1129.68
    80.5 1124.72   100.1 1114.65     124 1097.33   140.8 1087.24   174.3 1074.57
     191 1062.58   201.1 1056.36     218 1048.23   228.1 1042.18   244.9 1029.32
     257 1017.36   261.7 1013.75   268.5 1011.06   285.3 1008.99  292.971007.019
   305.5 1005.59  324.761007.018   331.4 1011.04   335.8 1011.92   406.5 1015.28
   500.7 1023.25   527.6 1033.01   561.4  1041.9   594.9 1045.48   613.3 1045.67
#Mann= 6 ,-1,0
       0      .1       0  242.02     .06       0  292.97    .045       0
  324.76     .06       0  377.02     .07       0  579.52     .05       0
Bank Sta=292.97,324.76
XS Rating Curve= 0 ,0
Exp/Cntr(USF)=0,0
Exp/Cntr=0.3,0.1

Type RM Length L Ch R = 1 ,6044    ,475.7,502.3,526.6
XS GIS Cut Line= 6
1652165.27198088505485.3968071491652251.20356755505522.878031388
1652331.40649113  505557.86024491652400.15176047505587.844436899
1652640.76053122505692.7907493111652726.69211788505730.271317393
#Sta/Elev= 30
       0 1131.37    27.9  1121.8    38.6 1120.05    74.6 1099.19    92.3 1090.57
   131.9 1077.52   156.7 1065.77   178.2 1059.09   196.1 1051.47   249.8  1034.7
     259 1029.24     282 1008.47  292.581001.614   296.5 1000.84  332.151001.614
   348.7 1003.61   381.1 1003.13   396.5 1004.27   407.3 1005.98   418.5 1010.84
   435.9 1011.84   446.6 1010.41   471.7 1016.19   488.3 1025.61   514.6 1044.83
   532.5 1055.84   546.9 1066.23   560.5 1077.74     597 1093.97   612.5 1104.26
#Mann= 5 ,-1,0
       0      .1       0  231.25     .06       0  292.58    .045       0
  332.15     .06       0  461.25      .1       0
Bank Sta=292.58,332.15
XS Rating Curve= 0 ,0
Exp/Cntr(USF)=0,0
Exp/Cntr=0.3,0.1

Type RM Length L Ch R = 1 ,5542    ,513.2,497.7,478.6
XS GIS Cut Line= 6
1652030.97172455505655.0103130641652120.71892039505827.695663229
1652143.06861322505904.6751680671652123.30290473506002.917097554
1652124.45972656506081.5045388041652189.22600122506267.885071561
#Sta/Elev= 30
       0 1094.94      58 1074.73   100.7 1057.69   142.6 1044.22     158 1040.27
   172.4 1039.53   186.9 1037.56   197.6 1034.46   204.4 1030.83   207.8 1027.64
   214.6 1019.56     227 1009.26   231.7 1006.18   237.6 1003.65   252.2 1001.64
   302.9  999.71  306.07998.1507   309.6  997.26   324.5  996.61  343.97 998.151
   353.1  999.98   409.3 1000.48     506 1003.29   519.3 1004.93   532.6 1008.79
   558.6 1009.62   563.7 1011.79   586.3  1025.8   614.6 1045.31   651.4 1064.95
#Mann= 5 ,-1,0
       0      .1       0  294.99     .06       0  306.07    .045       0
  343.97      .1       0  385.21     .06       0
Bank Sta=306.07,343.97
XS Rating Curve= 0 ,0
Exp/Cntr(USF)=0,0
Exp/Cntr=0.3,0.1

Type RM Length L Ch R = 1 ,5044    ,502.5,501.4,494.7
XS GIS Cut Line= 6
1651609.06180722505967.4604755641651648.98495573506054.833332315
1651686.60036606506136.2025921491651722.12752597506204.397337645
1651895.80237547506401.2306053941651957.51649089506471.803955063
#Sta/Elev= 30
       0  1071.9    57.8 1052.48    76.5 1044.31    89.4  1037.5   122.5 1041.81
   134.2 1040.71   159.8 1036.01   203.3 1026.71   229.2 1019.97     244 1013.22
   255.1 1004.46   262.6 1000.27   271.8  996.76  294.08994.3266   310.6  993.22
  321.61994.3278   328.1  996.29   363.1  996.34     397  1000.7   430.5 1002.52
     483 1007.29   520.2 1007.24   529.7 1010.96   542.4 1013.55   554.6 1013.32
   569.6 1009.37   574.5 1009.45   589.5 1015.49   612.2 1018.54   618.8 1017.65
#Mann= 6 ,-1,0
       0      .1       0  294.08    .045       0  321.61      .1       0
   372.6     .05       0   392.6     .06       0   575.1      .1       0
Bank Sta=294.08,321.61
XS Rating Curve= 0 ,0
Exp/Cntr(USF)=0,0
Exp/Cntr=0.3,0.1