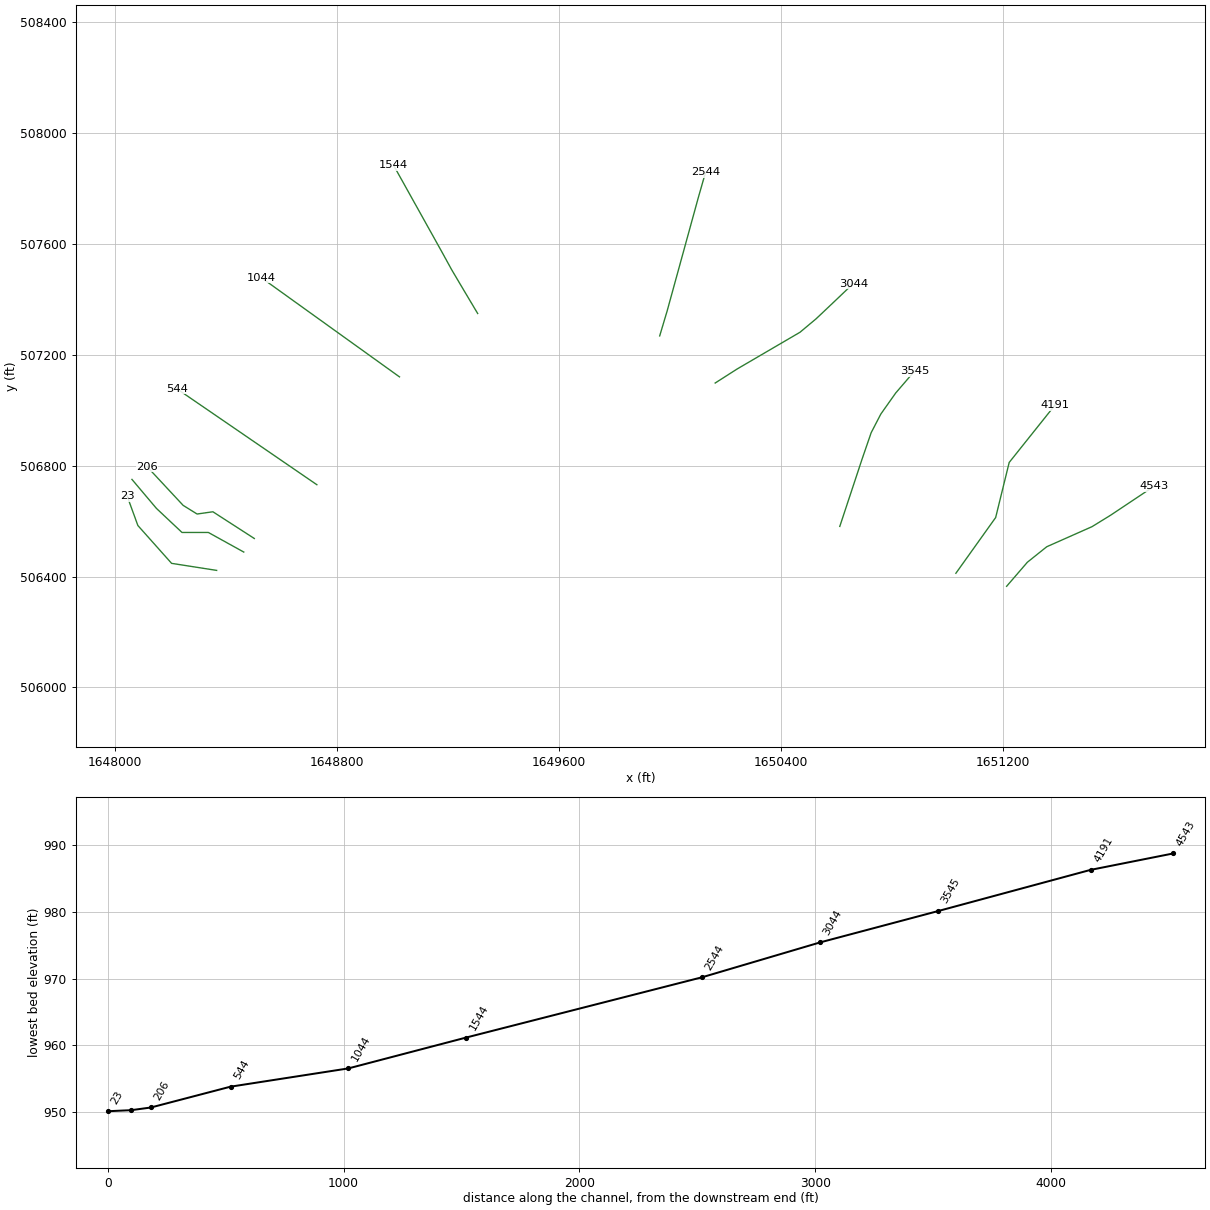
HEC-RAS study MidGraveCk.prj: MidGraveCk

--- MidGraveCk.g01 (geometry) --- (continued)

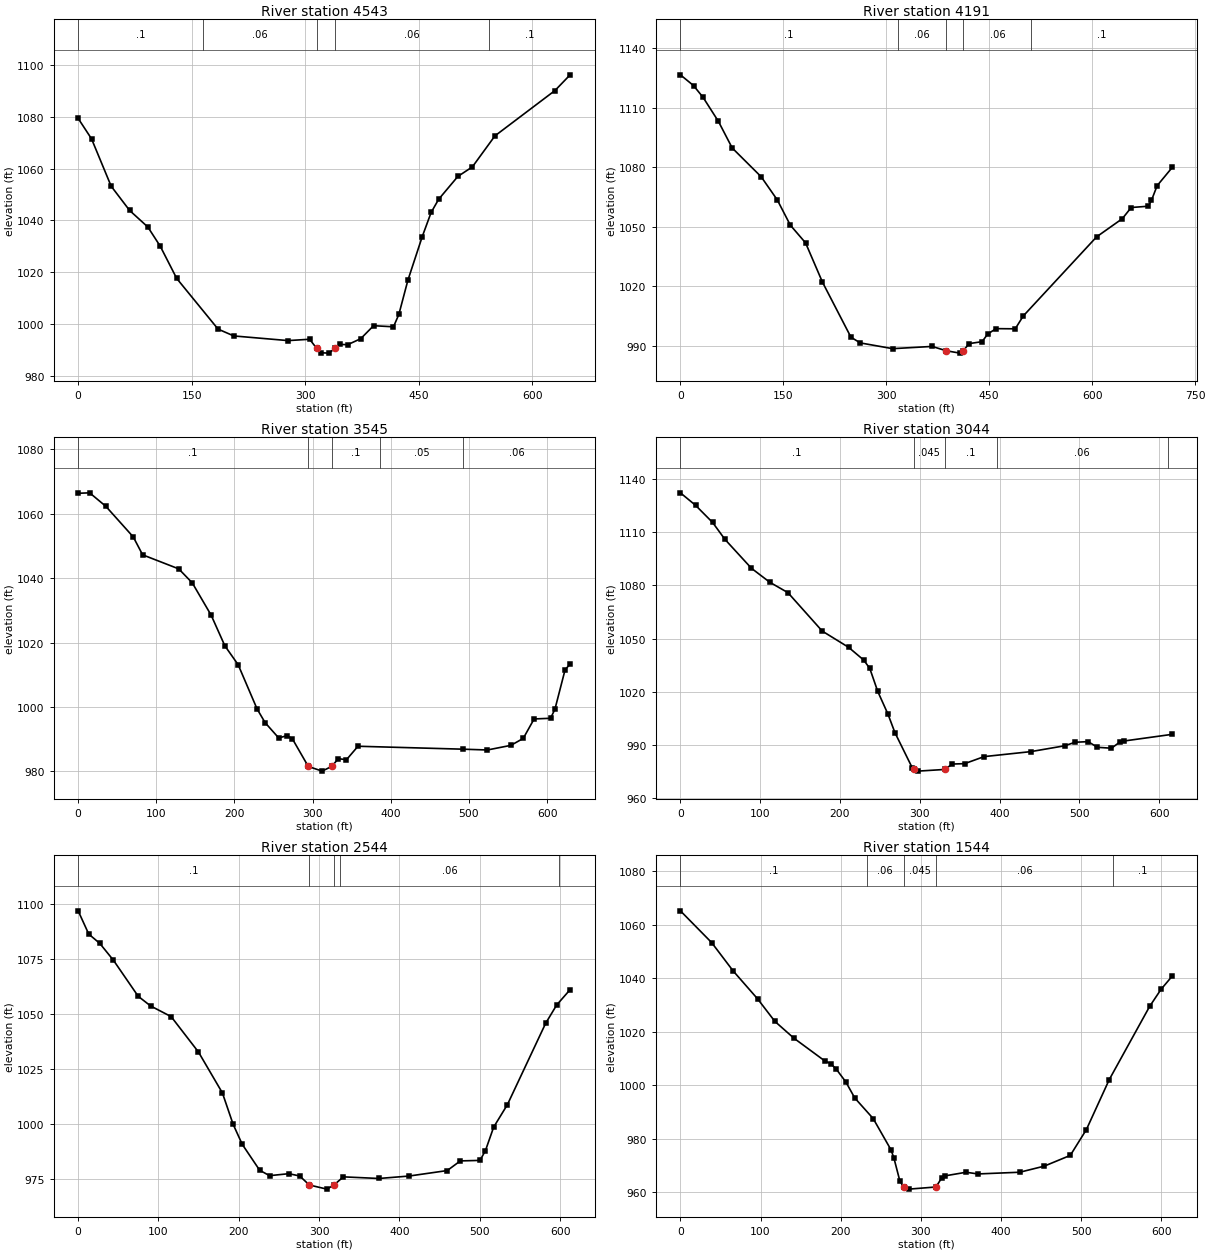
Type RM Length L Ch R = 1 ,4543    ,335.3,351.6,358.3
XS GIS Cut Line= 6
1651214.66823906506364.8760193141651289.51421797506451.647499308
1651359.33560064506507.4931881431651522.70305605506579.967452645
1651590.80921905506621.9394815561651746.39683439506725.753906474
#Sta/Elev= 30
       0 1079.45    17.7 1071.54    43.6 1053.25      68 1043.87    92.1 1037.46
   108.4 1030.07   130.2  1017.6   184.8  998.03   205.6  995.39   277.3  993.59
   305.7  994.11  315.16990.5512   320.1   988.9   330.9  988.75  339.35  990.55
   345.4  992.14   355.9     992   373.2  994.32   390.2  999.35   416.5  998.92
   423.6 1003.72   435.5  1016.9   454.4  1033.7   466.2  1043.1   476.2 1048.21
   501.5 1057.01   520.7 1060.71   550.5 1072.69   629.8 1090.21   649.8 1096.27
#Mann= 5 ,-1,0
       0      .1       0  164.59     .06       0  315.16    .045       0
  339.35     .06       0  542.74      .1       0
Bank Sta=315.16,339.35
XS Rating Curve= 0 ,0
Exp/Cntr(USF)=0,0
Exp/Cntr=0.3,0.1

Type RM Length L Ch R = 1 ,4191    ,640.2,646.4,638.9
XS GIS Cut Line= 4
1651031.73789182506411.8811906111651175.14597742506612.811676812
1651223.94578053506811.4965894521651389.61486067507018.931779968
#Sta/Elev= 30
       0 1126.62    19.1 1121.21      33 1115.28    55.4 1103.14    75.5 1089.73
   117.7 1075.22   141.2 1063.54   160.2 1050.81   182.4 1041.87     207 1022.08
   248.5  994.32     262  991.44   309.3  988.53   366.8  989.66  387.45987.4691
   407.3  986.28   412.2  987.47   420.6  991.07   439.6  992.06   447.8   995.9
   459.9  998.63   487.9  998.54   499.6 1005.01   606.5 1044.92   643.9 1054.07
   656.9 1059.71   681.7 1060.36   686.4  1063.3   694.7 1070.73   716.9 1080.01
#Mann= 5 ,-1,0
       0      .1       0  316.86     .06       0  387.45    .045       0
   412.2     .06       0  511.45      .1       0
Bank Sta=387.45,412.2
XS Rating Curve= 0 ,0
Exp/Cntr(USF)=0,0
Exp/Cntr=0.3,0.1

Type RM Length L Ch R = 1 ,3545    ,506.4,500.6,483
XS GIS Cut Line= 6
1650613.06379922506580.8227658871650693.59382188 506824.09032397
1650726.17643389506918.6409878881650761.09303072506986.082782149
1650814.51713647507061.6981164811650882.70991348507141.025385648
#Sta/Elev= 30
       0 1066.33    14.7 1066.47    35.4 1062.29    70.5 1052.79    82.5 1047.23
   128.7 1042.87     146 1038.53   170.2 1028.48   187.7 1018.99   204.7 1013.13
   228.9  999.41   239.2  995.15   256.6   990.4     267   991.1   273.9  990.21
  294.39981.5676   312.1  980.11  324.33981.5674   332.9  983.97   343.3  983.66
     358  987.83   492.2  986.92   523.5  986.67   553.6  988.11   569.4  990.26
   583.3   996.3   604.3  996.51   609.9  999.28   622.9 1011.53   629.4 1013.36
#Mann= 5 ,-1,0
       0      .1       0  294.39    .045       0  324.33      .1       0
  386.26     .05       0   492.2     .06       0
Bank Sta=294.39,324.33
XS Rating Curve= 0 ,0
Exp/Cntr(USF)=0,0
Exp/Cntr=0.3,0.1

Type RM Length L Ch R = 1 ,3044    ,486.7,500,513.3
XS GIS Cut Line= 6
1650163.69921239507097.9007999751650242.74039289507148.455816984
1650469.39610755507280.8699222211650527.65255272507329.494824976
1650592.35485114507390.6528391391650661.46593338 507456.53853415
#Sta/Elev= 30
       0 1132.18      19 1125.15    40.4 1115.47    55.8 1105.98    89.1 1089.66
     112 1081.83   134.8 1075.94   177.8  1054.3   210.8 1045.17   229.8 1037.97
   237.4 1033.27   247.3 1020.39   260.2  1007.5   268.9   997.1   290.6  977.31
  292.47976.3511   297.7  975.41  331.28976.3515   340.9   979.4   356.3  979.62
   380.7  983.59   439.1  986.39   481.6  989.68   494.8  991.68   511.1  992.02
   522.7  988.83   540.3  988.32   550.5  991.67   556.4   992.4   616.7  996.15
#Mann= 5 ,-1,0
       0      .1       0  292.47    .045       0  331.28      .1       0
  396.33     .06       0  611.24      .1       0
Bank Sta=292.47,331.28
XS Rating Curve= 0 ,0
Exp/Cntr(USF)=0,0
Exp/Cntr=0.3,0.1

Type RM Length L Ch R = 1 ,2544    ,975.5,1000,1007.2
XS GIS Cut Line= 6
1649963.58281472507267.7688985621649990.42823347507357.616815984
1650013.62963064507441.9847574831650060.03144072507610.720640481
1650103.11960913 507767.404054151650128.91975439 507857.53904447
#Sta/Elev= 30
       0 1096.71    13.2 1086.14    26.9 1081.92      44 1074.21    74.8 1057.85
    90.2 1053.47   115.8 1048.61   149.8 1032.51   179.6 1013.92   192.9   999.7
   204.3  990.55     226  978.77   238.3  976.31   262.3  977.21   275.8  976.17
  287.85 972.053   309.7  970.19  318.42972.0555   330.2  975.77   374.4  975.03
   411.8  976.13   459.5  978.63   475.8  983.02   500.3  983.25   507.1  987.73
   517.3  998.38   534.4 1008.59     582 1045.56   595.8 1053.93   612.5 1060.89
#Mann= 5 ,-1,0
       0      .1       0  287.85    .045       0  318.42      .1       0
  326.27     .06       0  598.77      .1       0
Bank Sta=287.85,318.42
XS Rating Curve= 0 ,0
Exp/Cntr(USF)=0,0
Exp/Cntr=0.3,0.1

Type RM Length L Ch R = 1 ,1544    ,488.3,500,506.5
XS GIS Cut Line= 6
1649307.21995422507348.6542354821649258.75974931507429.930647731
1649213.87171572507505.7083833071649177.73103997507571.524196565
1649129.02313213507658.8599798981649004.21137388 507882.65907298
#Sta/Elev= 30
       0 1065.25      39 1053.37    65.7 1042.82    96.3 1032.34   117.9  1023.9
   141.6 1017.63   180.2 1009.11   187.7 1008.09   194.7 1005.97   206.4 1001.28
   217.6  995.26   240.6  987.55   262.6  975.98   266.3  972.98   273.8  964.31
  278.47961.9584   285.1  961.16  318.95961.9596   326.4  965.49   329.8   966.1
   356.5  967.47   371.5  966.84   423.5  967.48   454.1  969.76   486.6  973.78
   506.7  983.45   535.2 1002.12   585.6 1029.49   599.9 1035.91     614 1040.91
#Mann= 5 ,-1,0
       0      .1       0   232.7     .06       0  278.47    .045       0
  318.95     .06       0  540.29      .1       0
Bank Sta=278.47,318.95
XS Rating Curve= 0 ,0
Exp/Cntr(USF)=0,0
Exp/Cntr=0.3,0.1

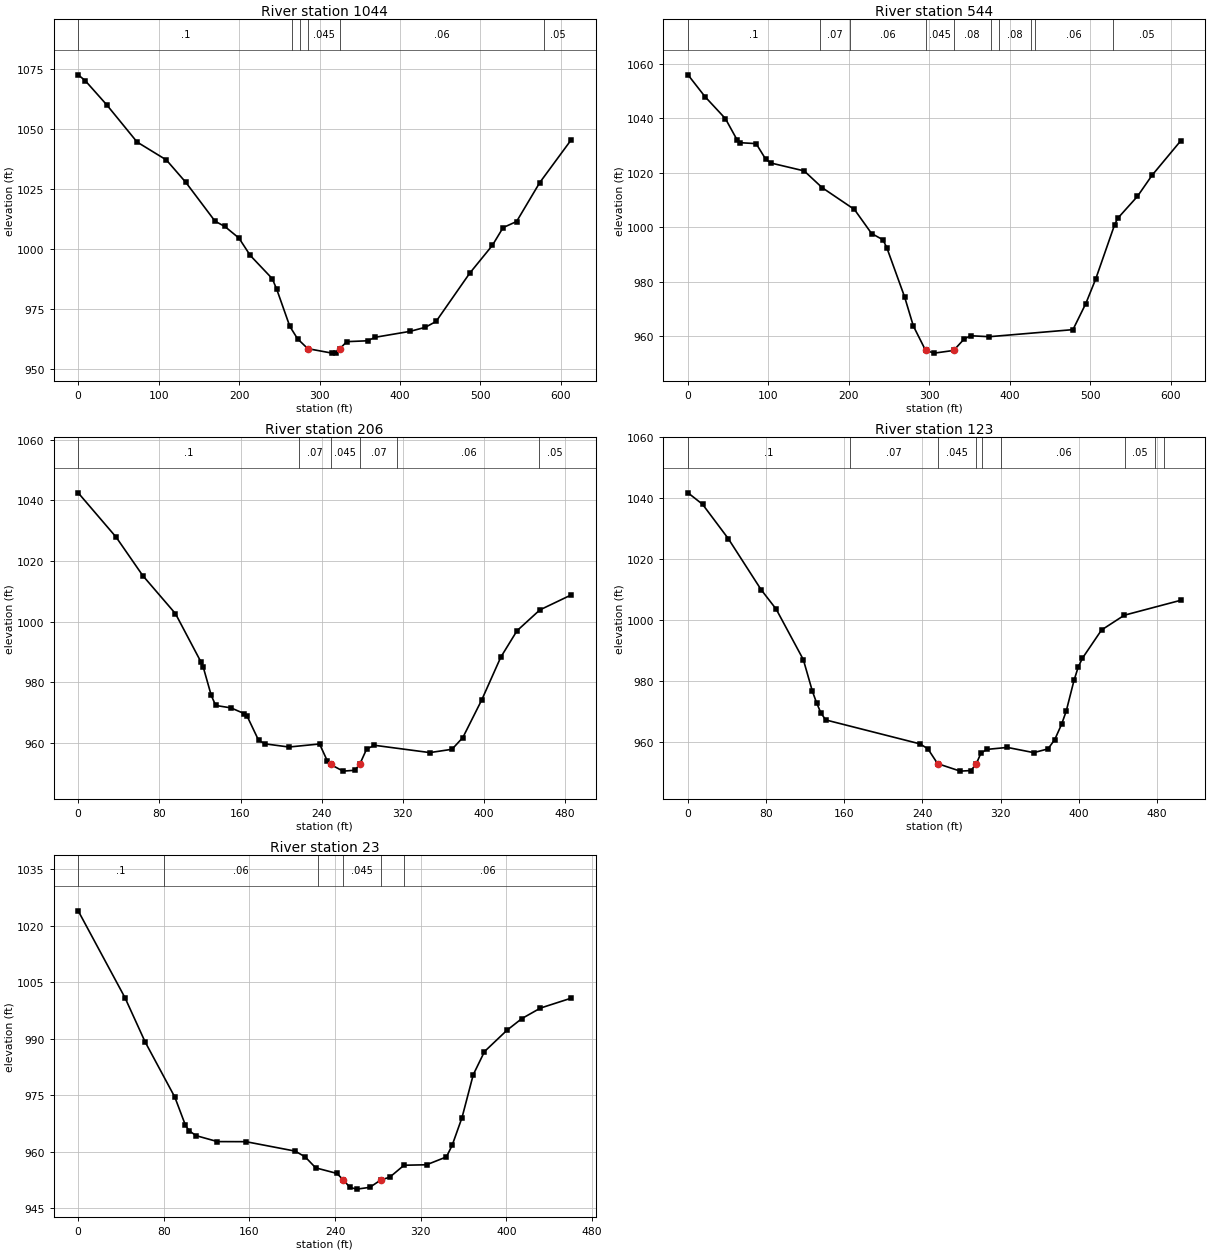
Type RM Length L Ch R = 1 ,1044    ,499.6,500,499.7
XS GIS Cut Line= 6
1649025.25070189507120.0871073161648949.09534238 507174.76285097
1648878.01674439507225.7932607231648817.09265363507269.533986896
 1648674.9361138507371.5951344821648527.70248438507477.301615983
#Sta/Elev= 30
       0 1072.46     8.6 1070.09    35.3 1060.03    73.2 1044.47   109.6    1037
   133.8 1027.66   170.1 1011.49   182.3 1009.28   199.8 1004.46   213.9  997.21
   241.2  987.56   246.8  983.11     263  967.71   272.7  962.48  285.36958.3954
   315.5  956.53   319.9   956.7  325.34 958.393   333.8  961.31   359.7  961.67
   369.1  963.13   412.5   965.6   431.3  967.27   444.8  969.71   486.6  989.81
   514.8 1001.42   528.1 1008.81   544.9 1011.36   573.6 1027.53   612.5 1045.26
#Mann= 6 ,-1,0
       0      .1       0  266.25     .06       0  276.25      .1       0
  285.36    .045       0  325.34     .06       0  578.75     .05       0
Bank Sta=285.36,325.34
XS Rating Curve= 0 ,0
Exp/Cntr(USF)=0,0
Exp/Cntr=0.3,0.1

Type RM Length L Ch R = 1 ,544     ,337,337.6,336.9
XS GIS Cut Line= 6
1648727.26015614 506731.237491311648515.88361038 506876.09579739
1648433.39525831506932.6258680671648371.52858414506975.023421064
1648299.35156314507024.4875609731648222.01838447507077.484502226
#Sta/Elev= 30
       0 1055.93    21.1 1047.94    46.5 1039.86    60.8 1032.19    64.8 1031.02
    84.7 1030.68    96.6 1024.96   103.1 1023.56   144.4 1020.67   166.8 1014.51
   206.9 1006.51   228.2  997.69   242.3   995.4   247.1  992.51   269.3  974.38
   280.1  963.75  295.37954.7741   306.1  953.79  330.15954.7728   343.2  958.95
   351.2  960.17   374.5  959.82   478.5  962.41   494.4  971.94   506.7  980.93
   530.3 1000.95   534.1 1003.26   558.6 1011.31   576.8 1019.06   612.5 1031.73
#Mann= 10 ,-1,0
       0      .1       0  163.75     .07       0  201.25     .06       0
  295.37    .045       0  330.15     .08       0  376.25     .07       0
  386.25     .08       0  426.25     .07       0  431.25     .06       0
  528.75     .05       0
Bank Sta=295.37,330.15
XS Rating Curve= 0 ,0
Exp/Cntr(USF)=0,0
Exp/Cntr=0.3,0.1

Type RM Length L Ch R = 1 ,206     ,83.7,83.4,78.4
XS GIS Cut Line= 5
1648501.76522249506537.2597906051648352.40243132506633.666683085
1648295.37300197506625.5196217481648245.13279039506656.750023537
1648114.77980901 506796.60790981
#Sta/Elev= 30
       0 1042.43    37.4 1027.82    63.6 1015.16    95.9 1002.58   121.2  986.54
   123.3  984.92   131.1  975.69   135.5  972.33   150.6  971.52   163.9   969.6
   166.5   968.8   177.9  960.77   184.5  959.65   207.7  958.62   237.9  959.62
   245.6  954.01  248.69 952.863   261.1  950.67   272.7  950.95  277.42 952.861
   284.3  957.95     292  959.19   346.6  956.78   368.4  957.87   379.1  961.73
   397.7  974.13   416.5  988.23   432.5  996.95     455 1003.82   485.7 1008.73
#Mann= 6 ,-1,0
       0      .1       0  217.77     .07       0  248.69    .045       0
  277.42     .07       0  314.54     .06       0  454.54     .05       0
Bank Sta=248.69,277.42
XS Rating Curve= 0 ,0
Exp/Cntr(USF)=0,0
Exp/Cntr=0.3,0.1

Type RM Length L Ch R = 1 ,123     ,101.4,99.5,97.6
XS GIS Cut Line= 5
1648463.74560292506488.3774225871648336.10830865506558.985287502
1648241.05925972506558.9852875021648148.72589791506645.887275089
1648060.46606677506750.441228905
#Sta/Elev= 30
       0 1041.75    14.9 1037.99    41.2 1026.72    74.9  1009.9    90.3 1003.51
   118.1  986.92   127.4  976.49   131.6  972.79   136.1  969.36     141   967.1
   237.6  959.22   245.6   957.6  255.53952.7336   278.7  950.27   289.7  950.46
  295.23952.7348   299.9  956.16   305.9  957.41     327  958.06     354  956.35
   368.6  957.58   375.5  960.66   382.5  965.68   387.2  969.97   395.2   980.1
   399.5  984.46   403.8  987.38   423.4  996.67   446.7 1001.52   504.5 1006.43
#Mann= 9 ,-1,0
       0      .1       0  165.87     .07       0  255.53    .045       0
  295.23     .06       0  300.91     .07       0  320.91     .06       0
  447.71     .05       0  477.71     .06       0  487.71     .05       0
Bank Sta=255.53,295.23
XS Rating Curve= 0 ,0
Exp/Cntr(USF)=0,0
Exp/Cntr=0.3,0.1

Type RM Length L Ch R = 1 ,23      ,,,
XS GIS Cut Line= 4
1648366.01138075506422.2177365811648203.49490432506447.625527747
1648081.87658551 506584.075348851648043.15962059506690.338580245
#Sta/Elev= 30
       0 1024.01    43.8  1000.9    62.5  989.23    90.3  974.53   100.2  967.08
   103.6  965.62   110.2  964.31   130.1  962.73   156.7  962.71   202.8   960.2
   212.1  958.66   221.9  955.76   241.7  954.28  247.76 952.556   253.9  950.55
   260.5  950.11   272.5  950.59  282.76 952.556   291.1  953.28   304.4  956.45
   325.5  956.58     344  958.66   349.4  961.75   358.6  969.11   369.1   980.5
   379.6  986.64   400.5  992.28   414.5   995.4   431.9  998.19   460.4  1000.8
#Mann= 6 ,-1,0
       0      .1       0      80     .06       0  224.49     .07       0
  247.76    .045       0  282.76     .07       0  304.49     .06       0
Bank Sta=247.76,282.76
XS Rating Curve= 0 ,0
Exp/Cntr(USF)=0,0
Exp/Cntr=0.3,0.1
LCMann Table=0

Chan Stop Cuts=-1
Use User Specified Reach Order=0
Composite Channel Slope=5